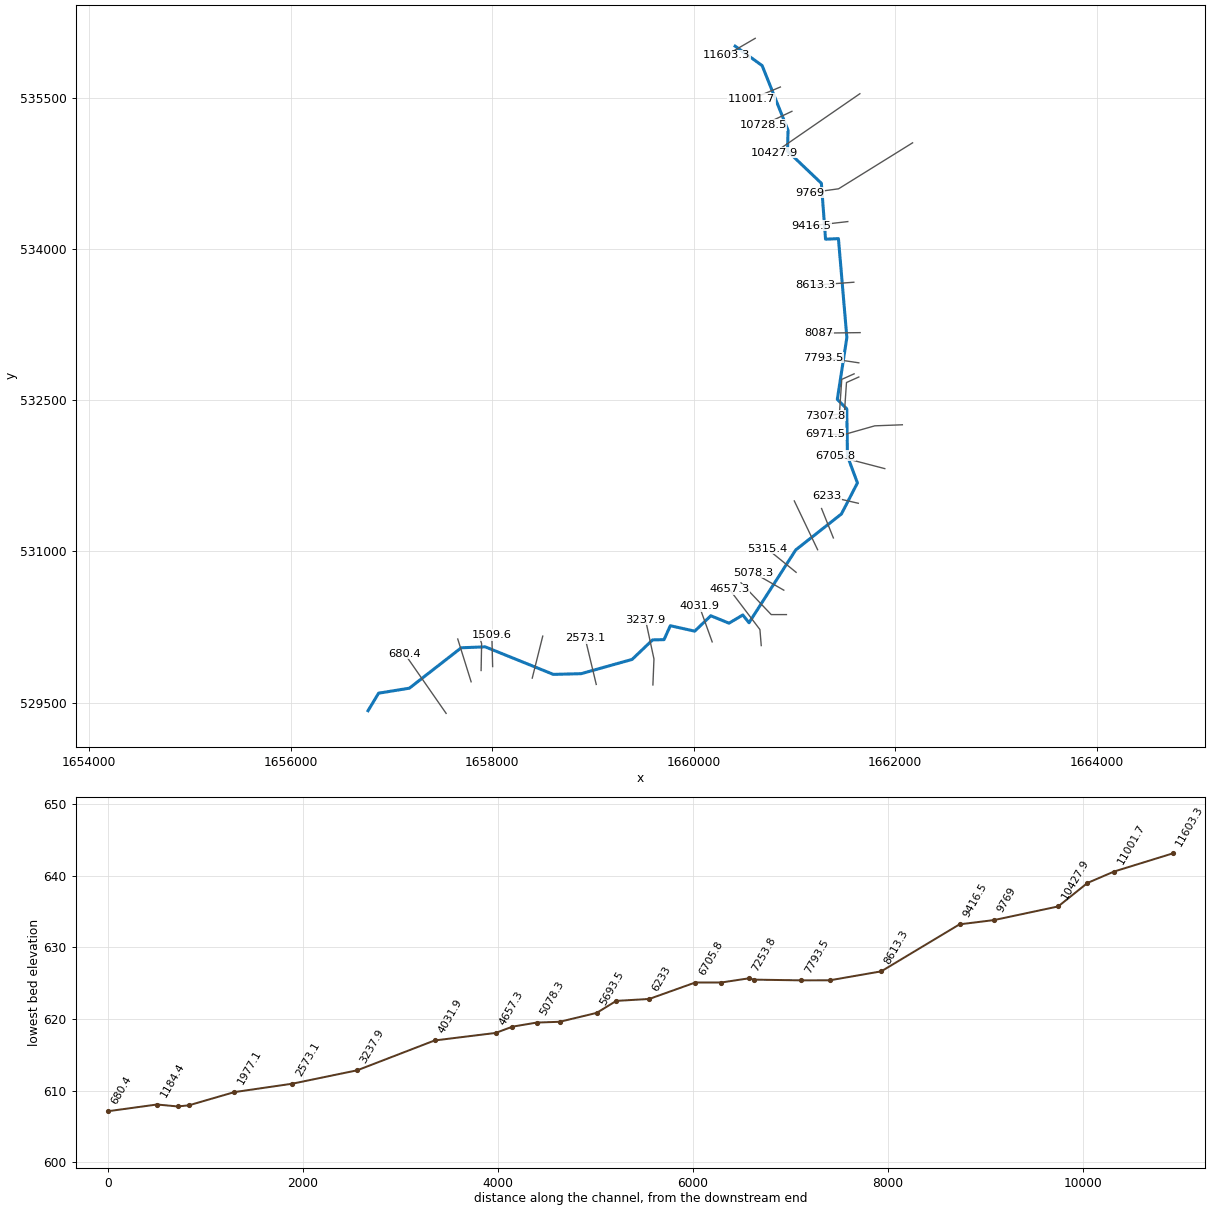
--- KilgoreCk.prj (project) ---

Proj Title=KilgoreCk
Current Plan=p01
Geom File=g01
Flow File=f01
Plan File=p01
DSS Export Rating Curves=0
DSS Export Rating Curve Sorted=0
DSS Export Volume Flow Curves=0
DXF OffsetX=0
DXF OffsetY=0
DXF ScaleX=0
DXF ScaleY=0

--- KilgoreCk.p01 (plan) ---

Plan Title=Floodplain
Program Version=4.00
Geom File=g01
Flow File=f01
K Sum by GR=0
Std Step Tol=0.01
Critical Tol=0.01
Num of Std Step Trials=20
Max Error Tol=0.3
Flow Tol Ratio=0.001
Split Flow NTrial=30
Split Flow Tol=0.02
Split Flow Ratio=0.02
Log Output Level=0
Friction Slope Method=1
Unsteady Friction Slope Method=2
Unsteady Bridges Friction Slope Method=1
Global Log Level=0
CheckData=False
Run HTab=0
Run UNet=0
Run PostProcess=0
UNET Theta=0
UNET Theta Warmup=0
UNET ZTol=0
UNET ZSATol=0
UNET MxIter=0
UNET MaxInSteps=0
UNET DtIC=0
UNET DtMin=0
UNET MaxCRTS=0
UNET WFStab=0
UNET SFStab=0
UNET WFX=0
UNET SFX=0
UNET DSS MLevel=0
UNET DZMax Abort=0
UNET Convert EG Bridges=0
UNET Use Existing IB Tables=0
UNET Froude Limit=0
UNET Froude Power=0
Write IC File=0
Echo Input=False
Echo Output=False
Write Detailed=0

--- KilgoreCk.f01 (steady flow) ---

Flow Title=NFF Regression Equation
Program Version=4.10
Number of Profiles= 1
Profile Names=P100yr
River Rch & RM=KilgoreCk,Main            ,11603.3
     886
River Rch & RM=KilgoreCk,Main            ,10728.5
     903
River Rch & RM=KilgoreCk,Main            ,10427.9
     907
River Rch & RM=KilgoreCk,Main            ,9769
     920
River Rch & RM=KilgoreCk,Main            ,9416.5
    1159
River Rch & RM=KilgoreCk,Main            ,8613.3
    1171
River Rch & RM=KilgoreCk,Main            ,8087
    1174
River Rch & RM=KilgoreCk,Main            ,7793.5
    1190
River Rch & RM=KilgoreCk,Main            ,6705.8
    1215
River Rch & RM=KilgoreCk,Main            ,6233
    1343
River Rch & RM=KilgoreCk,Main            ,5895.5
    1347
River Rch & RM=KilgoreCk,Main            ,5315.4
    1366
River Rch & RM=KilgoreCk,Main            ,3237.9
    1420
River Rch & RM=KilgoreCk,Main            ,1509.6
    1466
River Rch & RM=KilgoreCk,Main            ,1184.4
    1486
River Rch & RM=KilgoreCk,Main            ,680.4
    1487
Boundary for River Rch & Prof#=KilgoreCk,Main            , 1
Up Type= 0
Dn Type= 1
Dn Known WS=611.3
DSS Import GetInterval= 0
DSS Import GetPeak= 0
DSS Import FillOption= 0

--- KilgoreCk.g01 (geometry) ---

Geom Title=USGS 10m DEM
Program Version=4.10

River Reach=KilgoreCk       ,Main
Reach XY= 30
     1660412.149      536012.387     1660680.072       535819.64
     1660937.233      535177.279     1660931.808      534972.201
     1661268.179      534652.105     1661309.412      534097.635
      1661437.45       534103.06        1661521.      533121.941
     1661426.382      532509.093     1661520.132      532414.475
     1661527.077      531946.593     1661626.035        531680.1
     1661467.181      531371.941     1661014.056      531016.038
     1660549.646      530292.947     1660488.014      530370.204
     1660350.861      530288.607     1660170.306      530362.392
     1660010.584      530209.614     1659768.396      530263.434
     1659705.896      530125.413     1659592.181      530122.809
     1659389.056      529929.232      1658882.98      529787.739
     1658606.938      529780.795     1657929.855      530054.232
     1657692.875      530044.684     1657177.992      529644.055
     1656872.288      529594.192     1656767.346      529420.801

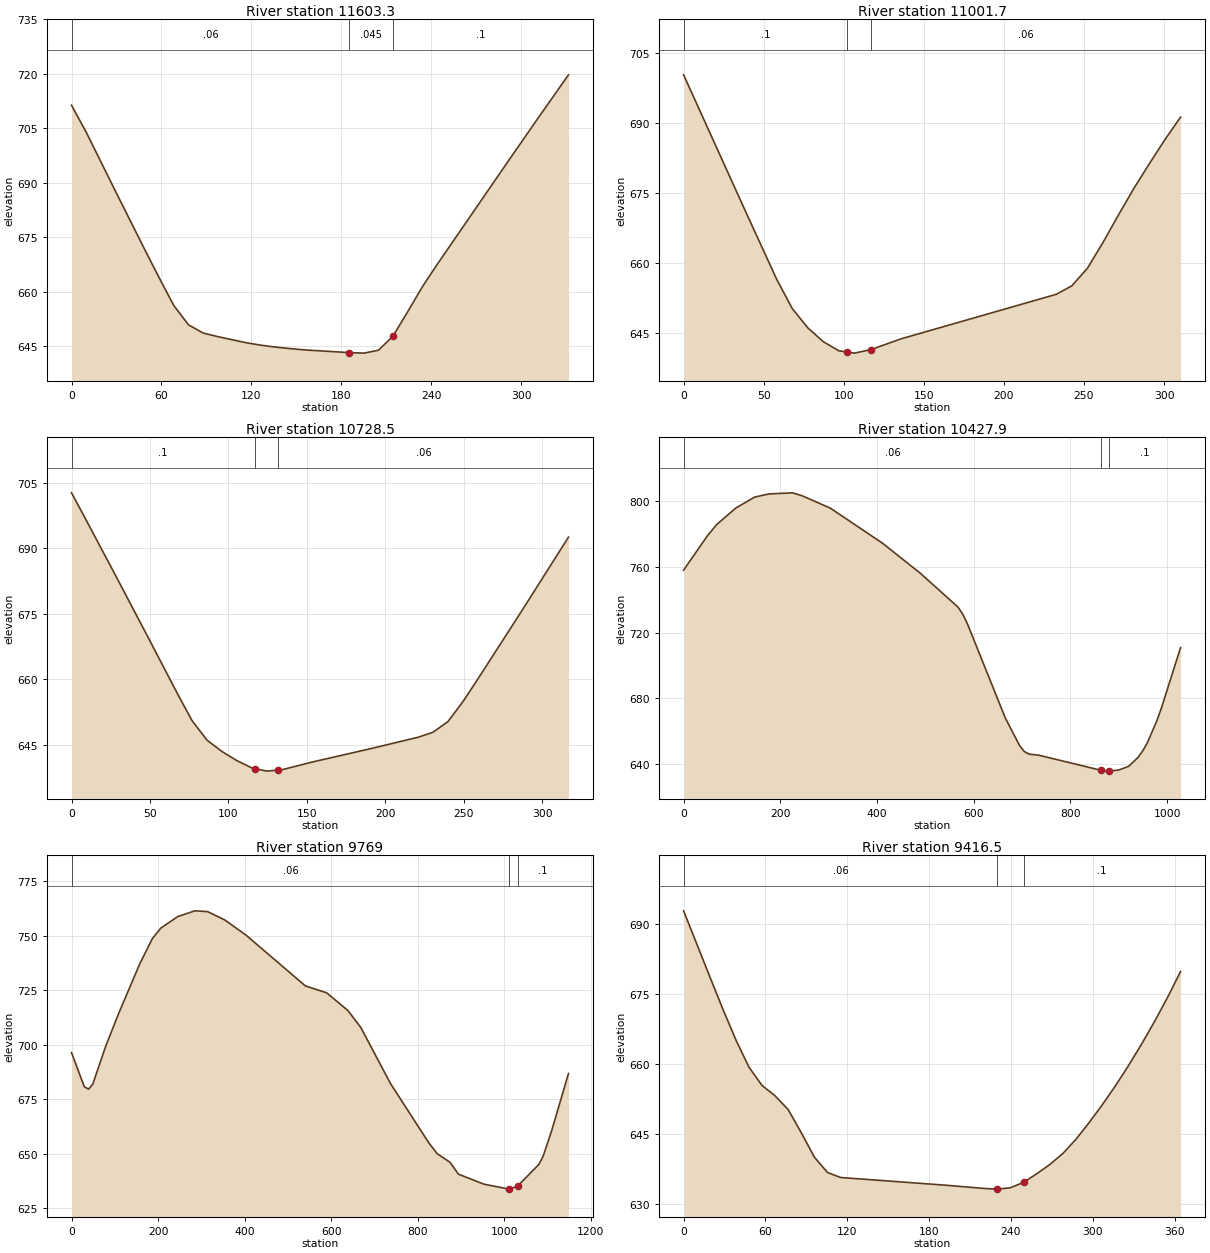
Type RM Length L Ch R = 1 ,11603.3 ,604.7,601.6,596.6
XS GIS Cut Line= 2
     1660611.096      536090.072     1660324.638      535923.405
#Sta/Elev= 24
       0  711.32     9.8  703.91    29.2  687.77    48.7  671.74    58.5  663.83
    68.2  656.25      78  650.93    87.7  648.68    97.5  647.68     117  645.96
   126.7   645.3   136.5  644.78   146.2  644.37     156  644.01   185.2  643.28
     195  643.14   204.7  643.94   214.4  647.83   224.2  654.54   233.9  661.35
   243.7  667.46   292.4  696.65   311.9  708.24   331.4  719.69
#Mann= 3 , 0 , 0
       0     .06       0   185.2    .045       0   214.4      .1       0
Bank Sta=185.2,214.4
XS Rating Curve= 0 ,0
Exp/Cntr=0.3,0.1

Type RM Length L Ch R = 1 ,11001.7 ,271.9,273.2,274
XS GIS Cut Line= 2
     1660861.046      535607.195     1660574.588      535487.837
#Sta/Elev= 20
       0  700.36    38.8  670.95    58.2  656.42    67.9  650.16    77.6  646.02
    87.3  643.05      97   641.1   102.1  640.84   106.7  640.61   117.1  641.38
   135.8  643.68   232.8  653.25   242.4  655.06   252.1  658.81   261.8  664.33
   271.5  670.25   281.2     676   290.9  681.32   300.6  686.48   310.3  691.28
#Mann= 3 , 0 , 0
       0      .1       0   102.1    .045       0   117.1     .06       0
Bank Sta=102.1,117.1
XS Rating Curve= 0 ,0
Exp/Cntr=0.3,0.1

Type RM Length L Ch R = 1 ,10728.5 ,296.4,300.6,305.3
XS GIS Cut Line= 2
      1660975.68      535366.113     1660689.221      535230.697
#Sta/Elev= 23
       0  702.69     9.6  696.28    28.8  683.29      48  670.18    67.2  656.96
    76.8  650.58    86.4  646.09      96  643.48   105.6  641.38   115.2   639.7
   116.9  639.58   124.8  639.01   131.9  639.26   134.4  639.35   153.6   641.1
     192  644.26   220.8  646.75   230.4   647.9     240  650.36   249.6  654.95
   259.2  660.18     288  676.23   316.8  692.55
#Mann= 3 , 0 , 0
       0      .1       0   116.9    .045       0   131.9     .06       0
Bank Sta=116.9,131.9
XS Rating Curve= 0 ,0
Exp/Cntr=0.3,0.1

Type RM Length L Ch R = 1 ,10427.9 ,671.2,658.9,643.5
XS GIS Cut Line= 2
     1661650.159      535540.593     1660803.805      534957.259
#Sta/Elev= 30
       0     758      49   778.8    68.5  785.77   107.7  795.75   146.8  802.44
   176.2  804.37   225.2  805.06   244.7  803.33   303.5  795.75   411.2  774.46
   489.5  756.17   567.8  735.47   577.6  731.14   587.4  725.12   665.7  667.88
   695.1  651.21   704.8  647.64   714.6  646.05   734.2  645.46   864.1  636.18
   879.1  635.75   881.1  635.73   900.6  636.45   920.2  638.61   939.8  644.02
   949.6  648.04   959.4  653.08     979  666.47   988.8  674.58  1027.9  710.85
#Mann= 3 , 0 , 0
       0     .06       0   864.1    .045       0   879.1      .1       0
Bank Sta=864.1,879.1
XS Rating Curve= 0 ,0
Exp/Cntr=0.3,0.1

Type RM Length L Ch R = 1 ,9769    ,352.5,352.5,351.6
XS GIS Cut Line= 3
     1662173.596      535053.613     1661438.905      534597.571
     1661157.971      534558.822
#Sta/Elev= 30
       0  696.38    29.5  680.77    39.3  679.64    49.1  681.89    78.6  699.09
   108.1  713.91   157.2  736.85   186.7  748.58   206.4  753.44   245.7  758.74
     285  761.35   314.4  760.98   353.8  757.21   402.9  750.27   540.4  726.93
   589.6  723.77   638.7  715.66   668.2  707.96     737  682.22   825.4  655.09
   845.1  650.03   874.5  646.13   894.1  640.67   952.7   636.1  1011.4  633.82
    1031  635.26  1079.9  645.15  1089.6  648.85  1109.2  660.43  1148.3  686.82
#Mann= 3 , 0 , 0
       0     .06       0  1011.4    .045       0    1031      .1       0
Bank Sta=1011.4,1031
XS Rating Curve= 0 ,0
Exp/Cntr=0.3,0.1

Type RM Length L Ch R = 1 ,9416.5  ,798.9,803.2,717.1
XS GIS Cut Line= 2
     1661530.367      534272.363     1661168.388      534230.697
#Sta/Elev= 29
       0  692.83    19.2  678.74    28.8  671.78    38.4  665.16    47.9  659.36
    57.5  655.44    67.1  653.21    76.7  650.26    86.3  645.31    95.9  640.08
   105.5   636.8   115.1  635.72   191.8  634.08   220.5  633.37   230.1  633.23
   239.7  633.53   249.3  634.69   258.9   636.5   268.5   638.5   278.1  640.86
   287.7   643.9   297.2  647.41   306.8   651.2   316.4  655.25     326  659.58
   335.6  664.18   345.2  669.06   354.8  674.25   364.4  679.84
#Mann= 3 , 0 , 0
       0     .06       0   230.1    .045       0   249.3      .1       0
Bank Sta=230.1,249.3
XS Rating Curve= 0 ,0
Exp/Cntr=0.3,0.1

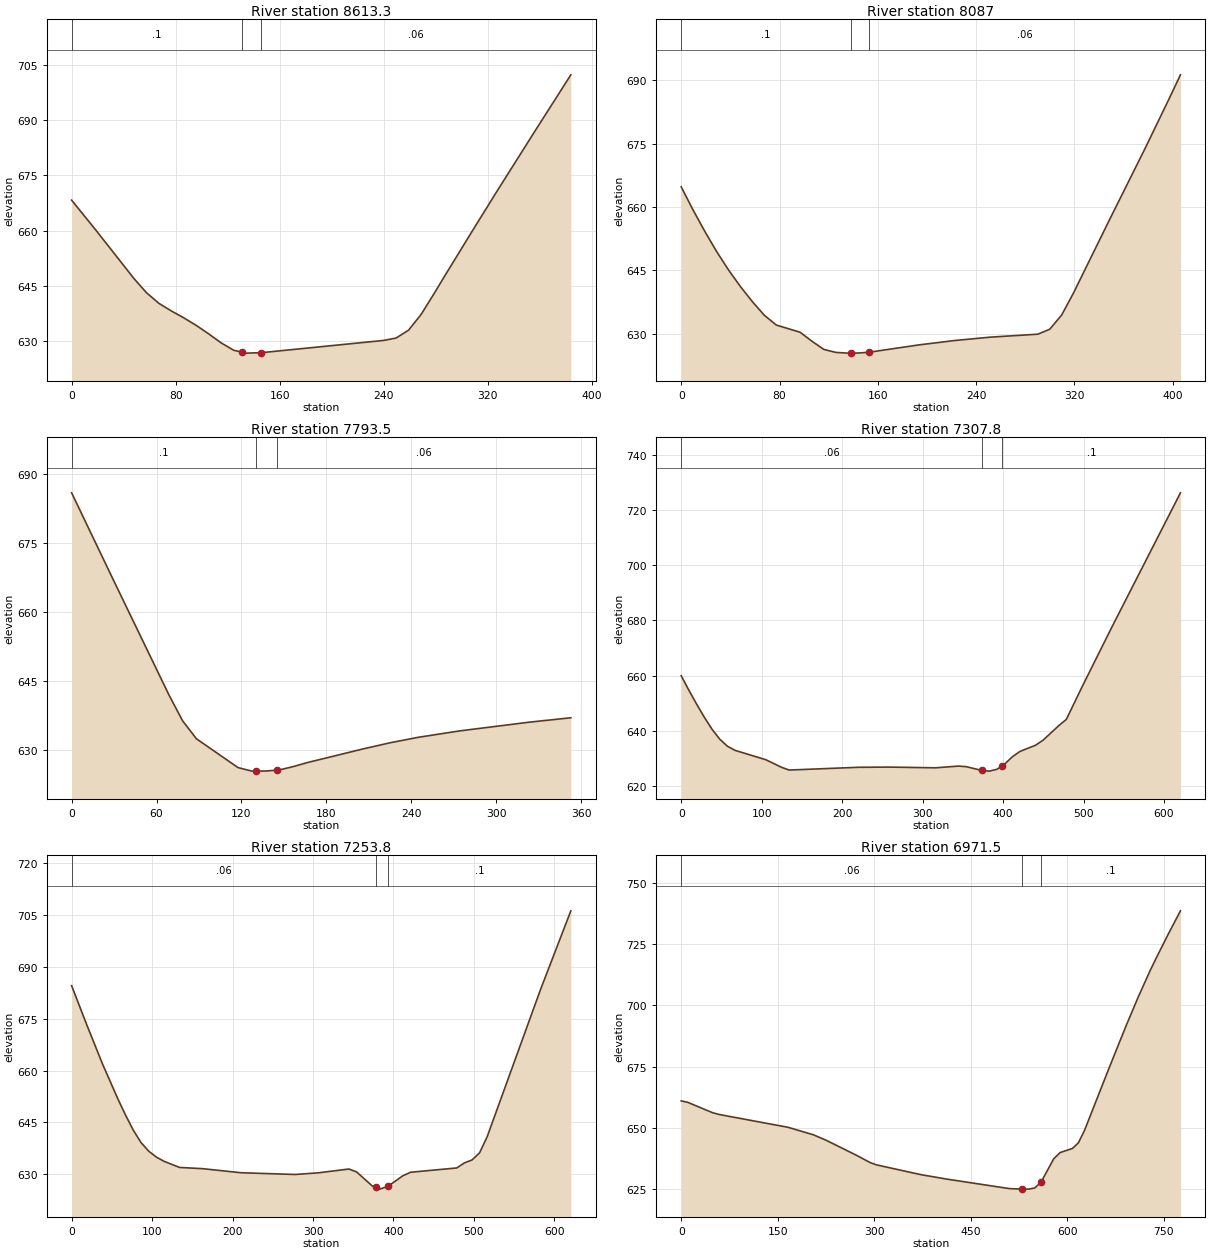
Type RM Length L Ch R = 1 ,8613.3  ,528.8,526.3,521.9
XS GIS Cut Line= 2
     1661590.263      533670.801     1661207.451      533642.155
#Sta/Elev= 24
       0  668.27    19.2  659.87      48  646.92    57.6  643.08    67.2  640.18
    76.8  638.11    86.4  636.23      96  634.16   105.6  631.85   115.2   629.4
   124.8  627.42   130.9  626.94   134.4  626.66   145.9  626.78   239.9  630.11
   249.5  630.76   259.1   632.9   268.7  637.16   278.3   642.6   287.9  648.22
   307.1  659.29   326.3  670.24   355.1  686.38   383.9  702.36
#Mann= 3 , 0 , 0
       0      .1       0   130.9    .045       0   145.9     .06       0
Bank Sta=130.9,145.9
XS Rating Curve= 0 ,0
Exp/Cntr=0.3,0.1

Type RM Length L Ch R = 1 ,8087    ,295,293.5,290.8
XS GIS Cut Line= 2
     1661652.763      533170.801     1661246.513      533165.593
#Sta/Elev= 28
       0  664.75     9.7  659.24    19.4  654.11      29  649.36    38.7     645
    48.4  641.08      58  637.55    67.7  634.35    77.4  632.05    96.7  630.36
   106.4  628.22   116.1  626.28   125.8  625.58   135.4  625.41   137.8  625.42
   145.1  625.45   152.8  625.62   193.5  627.36   222.5  628.39   251.5  629.19
   290.2  629.89   299.9  631.06   309.6  634.42   319.2  639.61   348.2  656.76
   377.3  673.72   396.6  685.32   406.3  691.27
#Mann= 3 , 0 , 0
       0      .1       0   137.8    .045       0   152.8     .06       0
Bank Sta=137.8,152.8
XS Rating Curve= 0 ,0
Exp/Cntr=0.3,0.1

Type RM Length L Ch R = 1 ,7793.5  ,196.8,485.7,521.6
XS GIS Cut Line= 2
     1661639.742      532871.322     1661290.784      532923.405
#Sta/Elev= 19
       0  685.95    29.4  667.06    68.6  642.09    78.4  636.36    88.2  632.44
   117.6  626.17   127.4   625.4     130  625.41   137.2  625.42     145  625.62
     147  625.67   156.8   626.4   166.6  627.26   205.8  630.22   225.4  631.59
     245  632.76   274.4  634.16   323.4  636.05   352.8  637.01
#Mann= 3 , 0 , 0
       0      .1       0     130    .045       0     145     .06       0
Bank Sta=130,145
XS Rating Curve= 0 ,0
Exp/Cntr=0.3,0.1

Type RM Length L Ch R = 1 ,7307.8  ,306.4,54,53.4
XS GIS Cut Line= 4
     1661592.867      532761.947     1661470.471      532707.259
     1661447.034      532363.509     1661306.409       532345.28
#Sta/Elev= 30
       0  659.99     9.6   654.7    19.2   649.7    28.7  644.99    38.3  640.64
    47.9  637.05    57.4   634.5      67     633   105.3  629.61   124.5   626.9
   134.1  625.89   220.2  626.89   258.5  626.96   315.9   626.7   344.6  627.32
   354.2  627.11   373.3  625.77   382.9   625.5   392.5  626.17   398.8  627.43
     402  628.07   411.6  630.72   421.2  632.66   440.3  634.86   449.9  636.75
     469  641.91   478.6  644.21   497.5  655.61   535.3  677.67   620.4  726.16
#Mann= 3 , 0 , 0
       0     .06       0   373.3    .045       0   398.8      .1       0
Bank Sta=373.3,398.8
XS Rating Curve= 0 ,0
Exp/Cntr=0.3,0.1

Type RM Length L Ch R = 1 ,7253.8  ,309.7,282.3,252.9
XS GIS Cut Line= 4
     1661639.742      532730.697     1661517.346      532676.009
     1661493.909      532332.259     1661353.284       532314.03
#Sta/Elev= 30
       0  684.56    19.2  673.01    38.3  661.95    57.4  651.83      67  647.12
    76.6  642.76    86.2  639.18    95.8  636.67   105.3  634.96   114.9  633.72
   134.1  631.96   162.8   631.6   210.6  630.42   277.6  629.92   306.3  630.39
   344.6   631.5   354.2  630.66   373.3  626.66   378.1  626.17   382.9  625.68
   393.1  626.49   411.6  629.54   421.2  630.56   478.6  631.81   488.1  633.27
   497.5  634.11     507  636.19   516.4  640.84   582.6  683.36   620.4  706.22
#Mann= 3 , 0 , 0
       0     .06       0   378.1    .045       0   393.1      .1       0
Bank Sta=378.1,393.1
XS Rating Curve= 0 ,0
Exp/Cntr=0.3,0.1

Type RM Length L Ch R = 1 ,6971.5  ,282.1,265.7,248.7
XS GIS Cut Line= 4
     1662072.034      532256.738     1661798.596      532246.322
     1661486.096       532157.78     1661309.013      532165.593
#Sta/Elev= 30
       0  661.09     9.8  660.53    48.9  656.25    58.6  655.56   166.1  650.31
   205.2  647.27   224.8  645.08   273.6  638.73   293.3  635.95   303.2  635.01
   372.1  631.02   411.4  629.24   509.8  625.32   529.5  625.12   539.4   625.1
   549.2  625.55   559.1  627.96   578.8  637.47   588.6     640   607.8  641.68
   617.1  643.98   626.4  648.91   663.7  673.75   682.4  685.97   691.7     692
   710.4  703.64     729  714.47   738.4  719.52     757  729.24   775.7  738.61
#Mann= 3 , 0 , 0
       0     .06       0   529.5    .045       0   559.1      .1       0
Bank Sta=529.5,559.1
XS Rating Curve= 0 ,0
Exp/Cntr=0.3,0.1

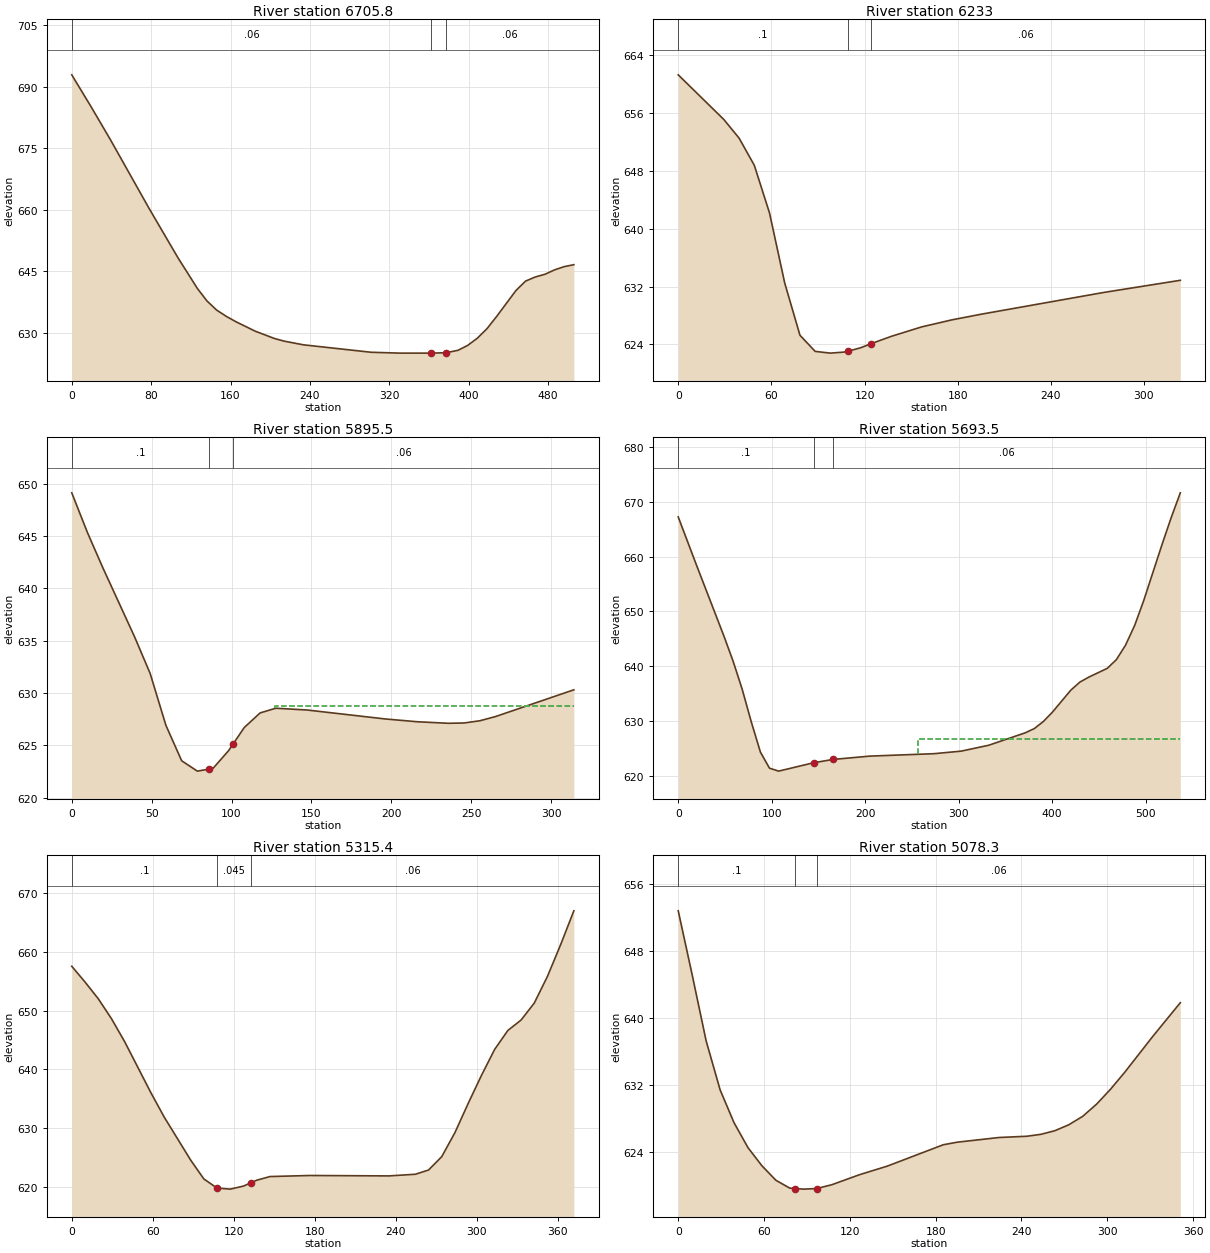
Type RM Length L Ch R = 1 ,6705.8  ,467.8,472.8,478
XS GIS Cut Line= 2
     1661897.555      531821.843     1661407.971      531949.447
#Sta/Elev= 30
       0  692.89    19.5   685.1    38.9  677.11    77.8   660.4     107  648.33
   126.5  640.88   136.2  637.82   145.9   635.6   155.7  634.06   165.4  632.75
   184.9  630.44   204.3  628.66     214  628.02   233.5  627.12   301.6  625.31
   330.8   625.1   362.4   625.1   377.4   625.2   389.2  625.79   398.9  626.98
   408.6  628.72   418.4  631.06   428.1  634.03   447.6  640.36   457.3  642.65
     467  643.64   476.8  644.31   486.5  645.38   496.2  646.17   505.9  646.64
#Mann= 3 , 0 , 0
       0     .06       0   362.4    .045       0   377.4     .06       0
Bank Sta=362.4,377.4
XS Rating Curve= 0 ,0
Exp/Cntr=0.3,0.1

Type RM Length L Ch R = 1 ,6233    ,359.4,337.5,315.5
XS GIS Cut Line= 2
     1661634.534      531478.093      1661319.43      531551.009
#Sta/Elev= 19
       0  661.32    29.4  655.13    39.2  652.56      49   648.8    58.8   642.2
    68.6   632.5    78.4  625.28    88.2  623.04      98   622.8   107.8  622.96
   109.4  623.06   117.6  623.55   124.4  624.12   137.2  625.12   156.8  626.43
   176.4  627.41     196  628.22   274.4  631.21   323.4  632.88
#Mann= 3 , 0 , 0
       0      .1       0   109.4    .045       0   124.4     .06       0
Bank Sta=109.4,124.4
XS Rating Curve= 0 ,0
Exp/Cntr=0.3,0.1

Type RM Length L Ch R = 1 ,5895.5  ,200.4,202,203.8
XS GIS Cut Line= 2
     1661387.138      531134.343     1661269.951      531426.009
#Sta/Elev= 23
       0  649.12     9.8  645.33    19.6  641.91    39.3  635.37    49.1  631.85
    58.9  626.92    68.8  623.52    78.6  622.53    85.9  622.72    88.4  622.79
    98.2  624.49   100.9   625.1     108   626.7   117.9  628.09   127.7  628.54
   147.3  628.37   196.5  627.51   216.1  627.25   235.8   627.1   245.6  627.13
   255.4  627.34   265.2  627.74   314.3   630.3
#Mann= 3 , 0 , 0
       0      .1       0    85.9    .045       0   100.9     .06       0
#XS Ineff= 2 , 0
                          127.18          628.73
Permanent Ineff=
       F       F
Bank Sta=85.9,100.9
XS Rating Curve= 0 ,0
Exp/Cntr=0.3,0.1

Type RM Length L Ch R = 1 ,5693.5  ,368,378,388
XS GIS Cut Line= 2
     1661230.888      531017.155     1660999.117       531501.53
#Sta/Elev= 30
       0  667.24    19.5  658.46    48.8  645.53    58.6  640.96    68.3  635.86
    78.1  629.86    87.9  624.32    97.6  621.39   107.4  620.85   144.8  622.38
     166  622.99     205  623.59   273.4  624.03   302.7   624.5     332  625.57
     371  627.83   380.8  628.61   390.5   629.9   400.3  631.63   419.8  635.61
   429.6   637.1   439.3  638.02   458.9  639.61   468.6  641.19   478.4  643.83
   488.2  647.45   497.9     652   517.4  662.18   527.2  667.09     537  671.64
#Mann= 3 , 0 , 0
       0      .1       0   144.8    .045       0     166     .06       0
#XS Ineff= 2 , 0
                           256.9           626.7
Permanent Ineff=
       F       F
Bank Sta=144.8,166
XS Rating Curve= 0 ,0
Exp/Cntr=0.3,0.1

Type RM Length L Ch R = 1 ,5315.4  ,233.6,237.1,240.6
XS GIS Cut Line= 2
     1661017.346      530793.197     1660728.284      531027.572
#Sta/Elev= 30
       0  657.54     9.8  654.87    19.6  652.03    29.4  648.63    39.2  644.71
    58.8  635.95    68.6  631.84    88.1  624.56    97.9  621.34   107.7  619.79
   117.5  619.61   127.3  620.13   133.1  620.72   137.1  621.13   146.9  621.75
   176.3  621.93     235  621.86   254.6  622.14   264.4  622.86   274.2  625.14
     284  629.24   293.8   634.2   303.6  638.95   313.4  643.39   323.2  646.62
     333  648.39   342.8  651.29   352.6  655.85   362.4  661.27   372.1  666.98
#Mann= 3 , 0 , 0
       0      .1       0   107.7    .045       0   133.1     .06       0
Bank Sta=107.7,133.1
XS Rating Curve= 0 ,0
Exp/Cntr=0.3,0.1

Type RM Length L Ch R = 1 ,5078.3  ,254.6,248,241.4
XS GIS Cut Line= 2
     1660894.951      530616.113     1660590.263      530790.593
#Sta/Elev= 28
       0  652.82     9.8  645.12    19.5  637.26    29.3  631.38      39  627.46
    48.8  624.46    58.5   622.3    68.3  620.56      78  619.62    81.8  619.57
    87.8   619.5    96.8  619.57   107.3  620.02   126.8  621.23   146.3  622.26
   185.3  624.81   195.1  625.12   224.3  625.68   243.8  625.83   253.6  626.06
   263.3  626.49   273.1   627.2   282.8  628.21   292.6  629.68   302.3  631.46
   312.1  633.46   331.6  637.73   351.1  641.82
#Mann= 3 , 0 , 0
       0      .1       0    81.8    .045       0    96.8     .06       0
Bank Sta=81.8,96.8
XS Rating Curve= 0 ,0
Exp/Cntr=0.3,0.1

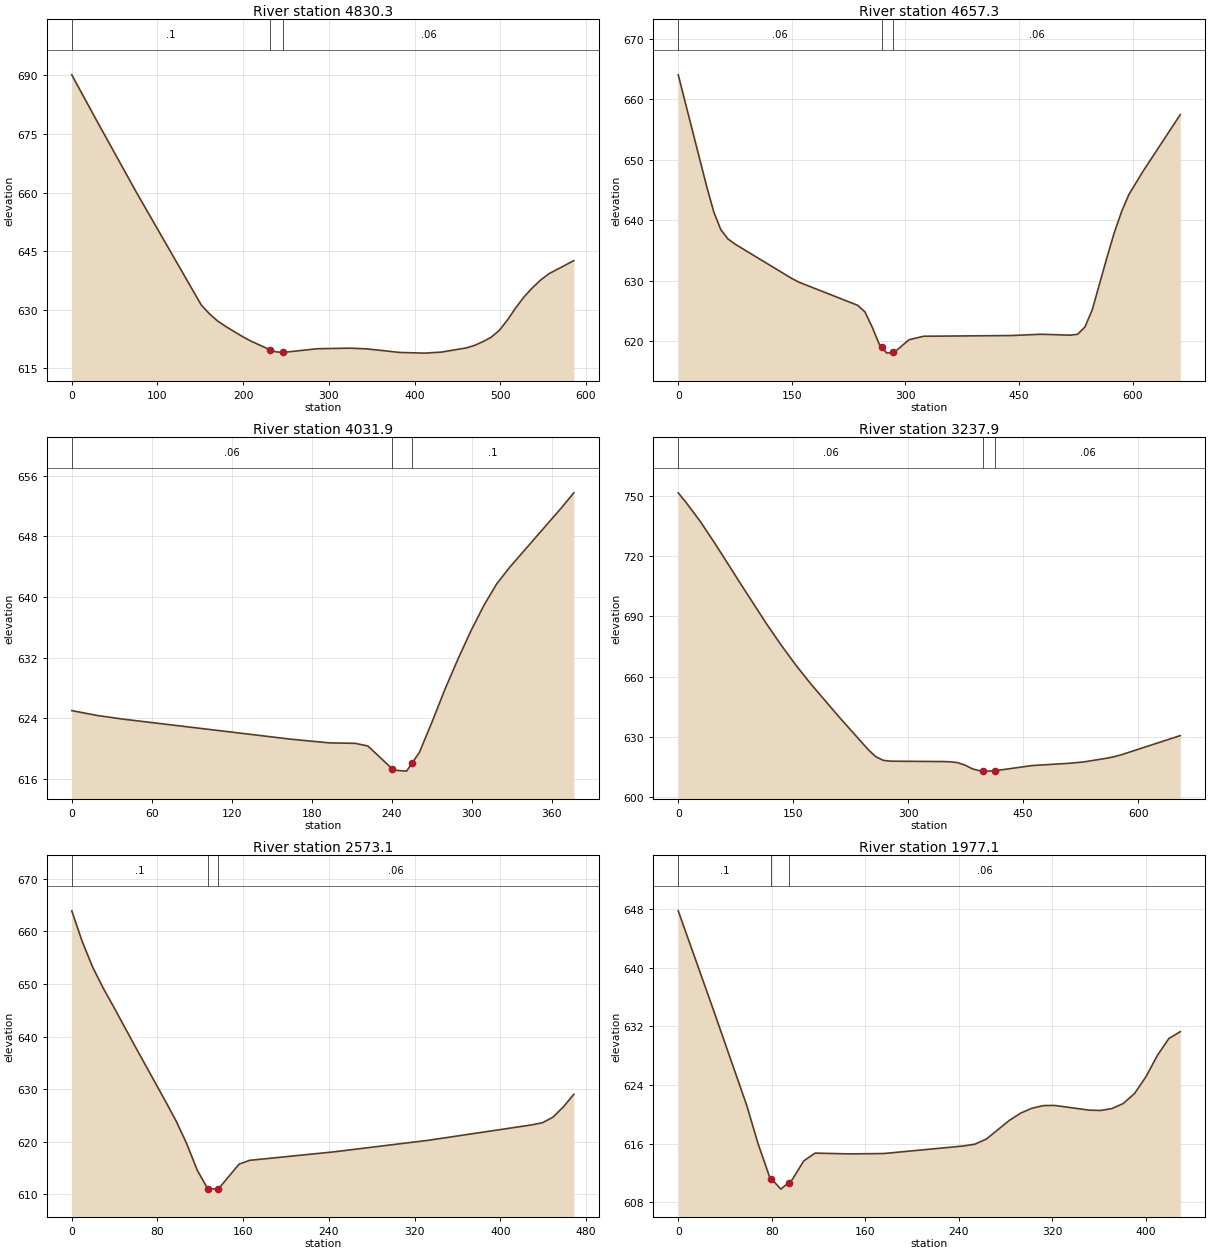
Type RM Length L Ch R = 1 ,4830.3  ,175.2,173,170.6
XS GIS Cut Line= 3
     1660920.992      530373.926     1660769.951      530373.926
     1660470.471       530689.03
#Sta/Elev= 30
       0  690.13    28.3  678.73    75.5  660.03     151  631.28   160.7  628.97
   170.4  627.11     180   625.7   199.3  623.15     209  622.01   231.3  619.79
     238  619.27   246.3   619.1   286.3  620.05   324.9   620.2   344.2  620.02
   382.9   619.1   411.9  618.93   431.2  619.19   460.2  620.26   469.8   620.9
   479.5  621.84   489.2  622.98   498.8  624.74   508.5  627.45   518.1  630.54
   527.8  633.34   537.5  635.64   547.1  637.64   556.8  639.25   585.8   642.6
#Mann= 3 , 0 , 0
       0      .1       0   231.3    .045       0   246.3     .06       0
Bank Sta=231.3,246.3
XS Rating Curve= 0 ,0
Exp/Cntr=0.3,0.1

Type RM Length L Ch R = 1 ,4657.3  ,602.4,625.4,615.1
XS GIS Cut Line= 3
     1660670.992      530066.634     1660657.971      530225.488
     1660353.284       530626.53
#Sta/Elev= 30
       0  664.07    37.5  645.65    46.9  641.42    56.2  638.47    65.6  636.94
      75  636.08     150  630.39   159.4  629.78   236.9  625.96   246.6  624.87
   256.2  622.33   265.9   619.4   268.8     619   275.6  618.05   283.8  618.16
   285.3  618.18   304.7  620.26     324  620.84   440.3  620.96     479  621.17
   517.8  621.02   527.4  621.17   537.1  622.38   546.8  625.25   566.2   633.9
   575.9  638.01   585.6   641.5   595.2   644.3   614.6  648.28     663   657.5
#Mann= 3 , 0 , 0
       0     .06       0   268.8    .045       0   283.8     .06       0
Bank Sta=268.8,283.8
XS Rating Curve= 0 ,0
Exp/Cntr=0.3,0.1

Type RM Length L Ch R = 1 ,4031.9  ,801.8,794.1,770.9
XS GIS Cut Line= 2
     1660184.013      530103.093     1660056.409      530457.259
#Sta/Elev= 21
       0  624.99    19.3  624.34    38.6  623.86   164.1  621.22     193  620.73
   212.4  620.67     222  620.32   240.1  617.33   241.3  617.13     251     617
   255.1  618.05   260.6  619.47   270.3  623.58   279.9  627.86   289.6  631.82
   299.2   635.5   308.9  638.86   318.5   641.7   328.2  643.89   366.8   651.7
   376.4  653.74
#Mann= 3 , 0 , 0
       0     .06       0   240.1    .045       0   255.1      .1       0
Bank Sta=240.1,255.1
XS Rating Curve= 0 ,0
Exp/Cntr=0.3,0.1

Type RM Length L Ch R = 1 ,3237.9  ,656.2,664.8,685.2
XS GIS Cut Line= 3
     1659595.471      529676.009     1659605.888      529933.822
     1659522.555      530321.843
#Sta/Elev= 30
       0  751.62     9.6  747.12    28.7  737.39    47.8  726.43      86  703.51
   114.7  686.58   133.8  675.93   152.9  665.98     172  656.75   210.2  639.68
   248.5  623.27     258  619.94   267.7  618.18   277.4  617.79   345.1   617.6
   354.8  617.49   364.5  617.06   374.2   615.8   383.9  613.94   393.5  612.98
   397.6  612.92   403.2  612.83   412.6  612.98   461.3   615.6   509.7  616.73
   529.1  617.42   558.1  619.21   567.8  619.93   577.4  620.92   654.9  630.55
#Mann= 3 , 0 , 0
       0     .06       0   397.6    .045       0   412.6     .06       0
Bank Sta=397.6,412.6
XS Rating Curve= 0 ,0
Exp/Cntr=0.3,0.1

Type RM Length L Ch R = 1 ,2573.1  ,606.7,596,584.9
XS GIS Cut Line= 2
     1659032.971      529681.218     1658923.596      530136.947
#Sta/Elev= 21
       0  663.93     9.8  658.07    19.5  653.21    29.3  649.24    39.1  645.66
    58.6  638.33    87.9  627.53    97.6  623.85   107.4  619.56   117.2  614.54
   126.9  611.05   136.7  610.96   156.2  615.72     166  616.44   244.1  618.04
     332  620.23   429.6  623.19   439.4   623.6   449.1  624.64   458.9  626.61
   468.7  629.02
#Mann= 3 , 0 , 0
       0      .1       0   126.9    .045       0   136.7     .06       0
Bank Sta=126.9,136.7
XS Rating Curve= 0 ,0
Exp/Cntr=0.3,0.1

Type RM Length L Ch R = 1 ,1977.1  ,460.5,467.5,474.4
XS GIS Cut Line= 2
     1658397.555      529743.718     1658501.721      530160.384
#Sta/Elev= 30
       0  647.79    29.3  634.62    58.6  621.22    68.3  615.98    78.1  611.48
    79.5  611.23    87.8  609.78    94.5  610.68    97.6  611.09   107.4  613.64
   117.1   614.7   146.4  614.59   175.7  614.64     244  615.67   253.8  615.92
   263.6  616.62   283.1  619.15   292.8  620.15   302.6  620.83   312.4  621.19
   322.1  621.21   351.4  620.57   361.2  620.52   370.9  620.78   380.7  621.47
   390.4  622.85   400.2  625.16     410  628.07   419.7  630.35   429.5  631.29
#Mann= 3 , 0 , 0
       0      .1       0    79.5    .045       0    94.5     .06       0
Bank Sta=79.5,94.5
XS Rating Curve= 0 ,0
Exp/Cntr=0.3,0.1

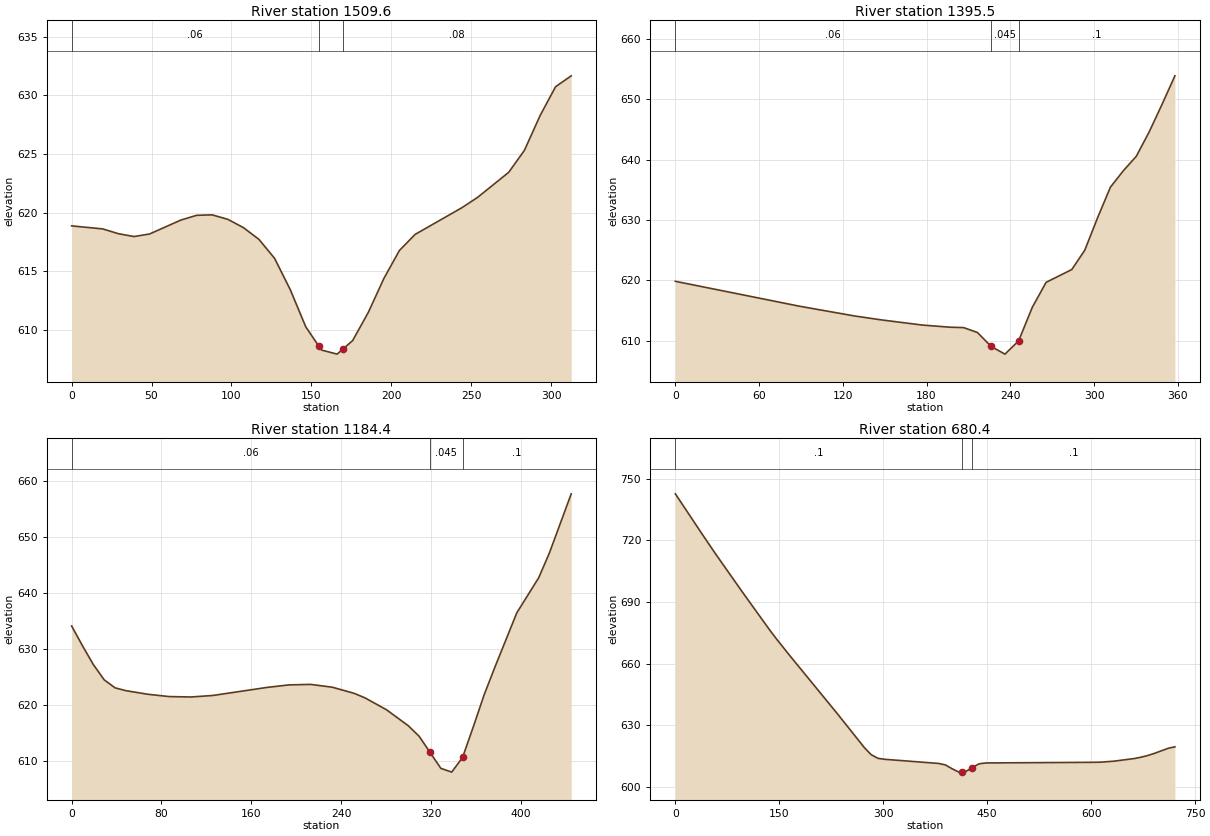
Type RM Length L Ch R = 1 ,1509.6  ,115.9,114.1,112.3
XS GIS Cut Line= 2
     1658004.326      529858.301     1657996.513      530170.801
#Sta/Elev= 30
       0  618.87    19.5  618.61    29.3   618.2    39.1  617.96    48.8  618.18
    68.4  619.37    78.2  619.77    87.9  619.81    97.7  619.43   107.5  618.72
   117.2  617.72     127   616.1   136.8  613.43   146.5  610.26   154.7   608.6
   156.3  608.28   166.1  607.93   169.7  608.36   175.8  609.08   185.6  611.48
   195.4  614.39   205.1  616.77   214.9  618.14   244.2  620.42     254   621.3
   273.5  623.44   283.3  625.31   293.1  628.27   302.8  630.74   312.6  631.67
#Mann= 3 , 0 , 0
       0     .06       0   154.7    .045       0   169.7     .08       0
Bank Sta=154.7,169.7
XS Rating Curve= 0 ,0
Exp/Cntr=0.3,0.1

Type RM Length L Ch R = 1 ,1395.5  ,203.8,211.1,218.4
XS GIS Cut Line= 3
     1657889.742      529819.238     1657894.951      530084.863
     1657868.909      530173.405
#Sta/Elev= 22
       0  619.84    88.6  615.73   127.9  614.12   147.6  613.45   177.1  612.59
   196.8  612.24   206.6  612.17   216.5  611.36   226.3  609.05   236.2  607.78
     246  609.98   255.8  615.54   265.7  619.67   284.1  621.79   293.4  624.99
   302.6  630.38   311.8  635.44     321  638.14   330.3  640.54   339.5  644.56
   348.7  649.11     358  653.87
#Mann= 3 , 0 , 0
       0     .06       0   226.3    .045       0     246      .1       0
Bank Sta=226.3,246
XS Rating Curve= 0 ,0
Exp/Cntr=0.3,0.1

Type RM Length L Ch R = 1 ,1184.4  ,496.9,504,510.8
XS GIS Cut Line= 2
     1657790.784      529707.259     1657657.971      530131.738
#Sta/Elev= 30
       0  634.17     9.7  630.62    19.3  627.28      29  624.54    38.7  623.11
    48.3  622.61    67.7  621.97      87  621.55   106.4  621.48   125.7  621.75
     174  623.19   193.4  623.64   212.7  623.73     232  623.23   251.4  622.14
   261.1  621.33   280.4  619.19   299.7  616.35   309.4  614.46   319.1  611.58
   328.7  608.73   338.4  608.05   348.1  610.69   357.7   616.2   367.4  621.94
   377.1  626.94   396.4  636.54   415.8  642.77   425.4  647.23   444.8  657.79
#Mann= 3 , 0 , 0
       0     .06       0   319.1    .045       0   348.1      .1       0
Bank Sta=319.1,348.1
XS Rating Curve= 0 ,0
Exp/Cntr=0.3,0.1

Type RM Length L Ch R = 1 ,680.4   ,675,680.4,684
XS GIS Cut Line= 2
     1657542.459      529394.009       1657130.7      529985.778
#Sta/Elev= 30
       0  742.63      39  722.85    58.4  713.21    97.4  694.49   136.4   676.2
   146.1   671.9   165.6  663.66   233.8  635.55   272.8  619.03   282.5  615.62
   292.3  613.83     302  613.36     380  611.33   389.7  610.62   399.4  608.74
   409.2  607.11   413.4  607.21   418.9  607.35   428.4  609.36   438.4  611.16
   448.1  611.58     604  611.89   613.8  611.96   633.2  612.45   662.5  613.74
   672.2  614.39     682  615.23   691.7  616.29   711.2  618.72   720.9  619.44
#Mann= 3 , 0 , 0
       0      .1       0   413.4    .045       0   428.4      .1       0
Bank Sta=413.4,428.4
XS Rating Curve= 0 ,0
Exp/Cntr=0.3,0.1

Chan Stop Cuts=-1
Use User Specified Reach Order=0
Composite Channel Slope=5